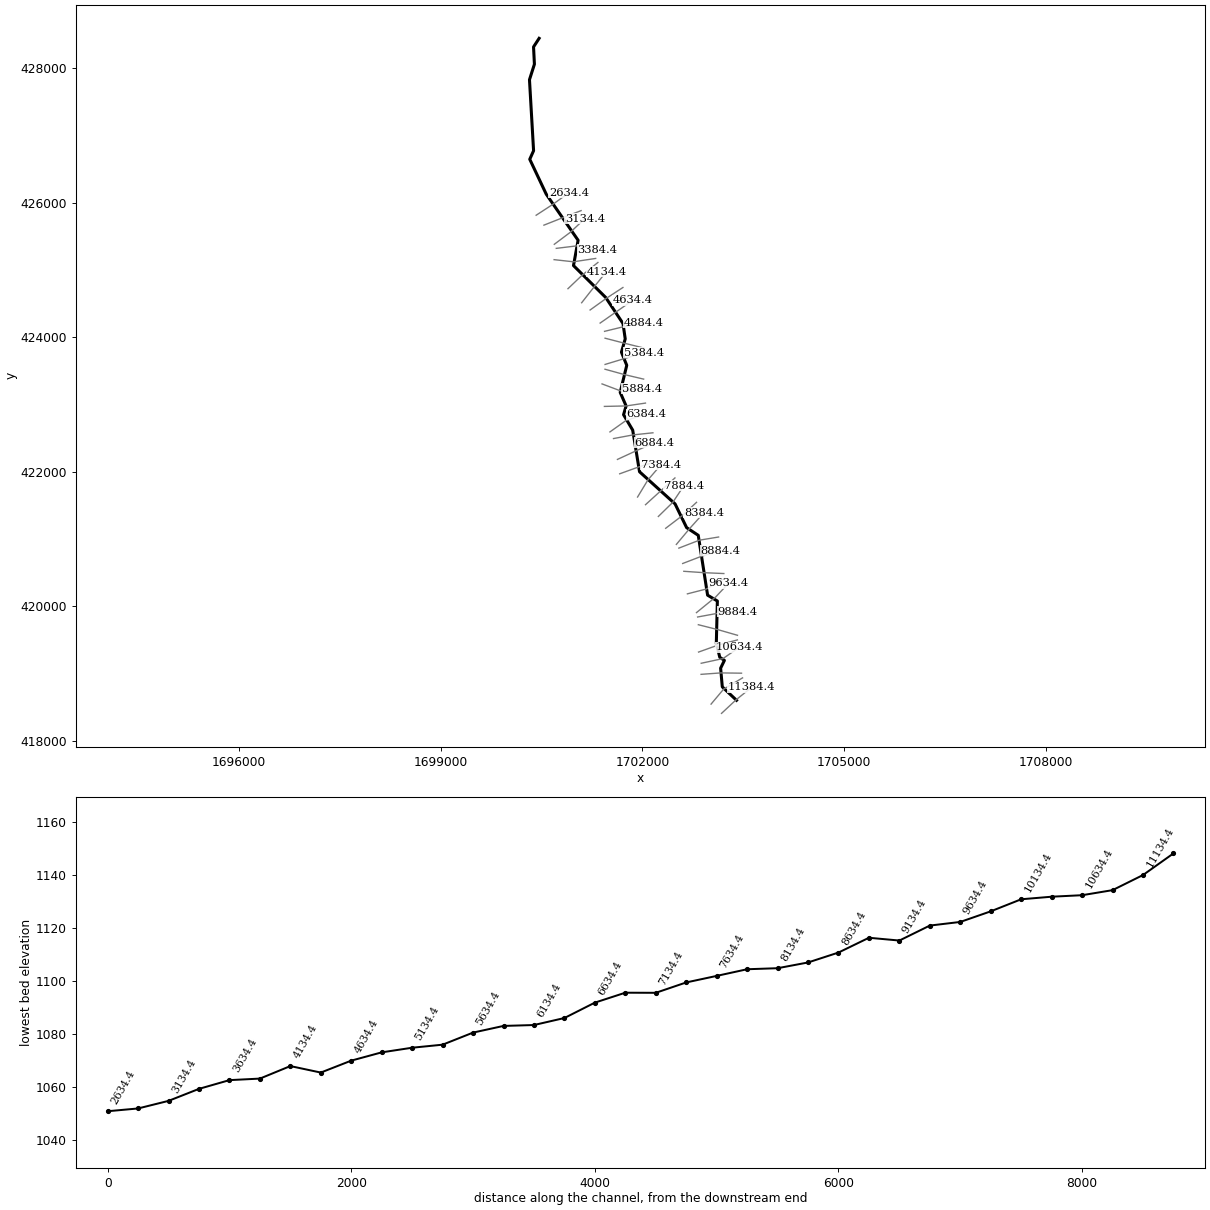
--- RUSHRN2.prj (project) ---

Proj Title=RUSHRN2
Current Plan=p01
Geom File=g01
Flow File=f01
Plan File=p01
DSS Export Rating Curves=0
DSS Export Rating Curve Sorted=0
DSS Export Volume Flow Curves=0
DXF OffsetX=0
DXF OffsetY=0
DXF ScaleX=0
DXF ScaleY=0

--- RUSHRN2.p01 (plan) ---

Plan Title=Floodplain
Program Version=4.00
Geom File=g01
Flow File=f01
K Sum by GR=0
Std Step Tol=0.01
Critical Tol=0.01
Num of Std Step Trials=20
Max Error Tol=0.3
Flow Tol Ratio=0.001
Split Flow NTrial=30
Split Flow Tol=0.02
Split Flow Ratio=0.02
Log Output Level=0
Friction Slope Method=1
Unsteady Friction Slope Method=2
Unsteady Bridges Friction Slope Method=1
Global Log Level=0
CheckData=False
Run HTab=0
Run UNet=0
Run PostProcess=0
UNET Theta=0
UNET Theta Warmup=0
UNET ZTol=0
UNET ZSATol=0
UNET MxIter=0
UNET MaxInSteps=0
UNET DtIC=0
UNET DtMin=0
UNET MaxCRTS=0
UNET WFStab=0
UNET SFStab=0
UNET WFX=0
UNET SFX=0
UNET DSS MLevel=0
UNET DZMax Abort=0
UNET Convert EG Bridges=0
UNET Use Existing IB Tables=0
UNET Froude Limit=0
UNET Froude Power=0
Write IC File=0
Echo Input=False
Echo Output=False
Write Detailed=0

--- RUSHRN2.f01 (steady flow) ---

Flow Title=Flow
Program Version=4.00
Number of Profiles=1
Profile Names=F01pct
River Rch & RM=RUSHRN2,Main      ,11384.4
358.9476
River Rch & RM=RUSHRN2,Main      ,10884.4
581.7510
River Rch & RM=RUSHRN2,Main      ,10634.4
585.1166
River Rch & RM=RUSHRN2,Main      ,10384.4
588.9331
River Rch & RM=RUSHRN2,Main      ,10134.4
602.1453
River Rch & RM=RUSHRN2,Main      ,9884.4
606.5842
River Rch & RM=RUSHRN2,Main      ,9384.4
612.0384
River Rch & RM=RUSHRN2,Main      ,9134.4
615.6461
River Rch & RM=RUSHRN2,Main      ,8884.4
619.6926
River Rch & RM=RUSHRN2,Main      ,8634.4
672.4662
River Rch & RM=RUSHRN2,Main      ,8384.4
675.2295
River Rch & RM=RUSHRN2,Main      ,7884.4
677.5244
River Rch & RM=RUSHRN2,Main      ,7634.4
714.2214
River Rch & RM=RUSHRN2,Main      ,7384.4
718.1279
River Rch & RM=RUSHRN2,Main      ,7134.4
721.9066
River Rch & RM=RUSHRN2,Main      ,6884.4
831.7683
River Rch & RM=RUSHRN2,Main      ,6384.4
834.0030
River Rch & RM=RUSHRN2,Main      ,6134.4
839.0504
River Rch & RM=RUSHRN2,Main      ,5884.4
842.8139
River Rch & RM=RUSHRN2,Main      ,5634.4
900.6670
River Rch & RM=RUSHRN2,Main      ,5384.4
903.4891
River Rch & RM=RUSHRN2,Main      ,4884.4
906.8814
River Rch & RM=RUSHRN2,Main      ,4634.4
936.7835
River Rch & RM=RUSHRN2,Main      ,4384.4
940.2488
River Rch & RM=RUSHRN2,Main      ,4134.4
944.8721
River Rch & RM=RUSHRN2,Main      ,3884.4
948.1076
River Rch & RM=RUSHRN2,Main      ,3384.4
954.1702
River Rch & RM=RUSHRN2,Main      ,3134.4
977.2958
River Rch & RM=RUSHRN2,Main      ,2884.4
1033.217
River Rch & RM=RUSHRN2,Main      ,2634.4
1036.118
River Rch & RM=RUSHRN2,Main      ,2384.4
1048.194
River Rch & RM=RUSHRN2,Main      ,1884.4
1051.235
River Rch & RM=RUSHRN2,Main      ,1634.4
1053.783
Boundary for River Rch & Prof#=RUSHRN2,Main      ,1
Up Type=0
Dn Type=3
Dn Slope=0.004284

--- RUSHRN2.g01 (geometry) ---

Geom Title=Geometry
Program Version=4.00

River Reach=RUSHRN2     ,Main
Reach XY= 30
     1703400.657      418598.960     1703188.867      418798.869
     1703164.072      419076.779     1703220.377      419192.488
     1703151.675      419237.945     1703100.019      419445.603
     1703115.515      420075.290     1702970.362      420162.072
     1702831.407      421052.106     1702658.359      421166.266
     1702486.861      421519.077     1701958.420      421996.895
     1701856.658      422616.251     1701720.802      422845.087
     1701758.575      422975.906     1701670.599      423177.688
     1701768.261      423579.636     1701689.163      423774.961
     1701745.661      423972.707     1701712.537      424201.059
     1701455.807      424587.962     1700976.438      425062.682
     1701044.852      425438.924     1700571.104      426124.585
     1700326.130      426643.295     1700382.993      426770.245
     1700321.956      427826.280     1700395.308      428056.666
     1700382.394      428313.914     1700465.415      428441.413

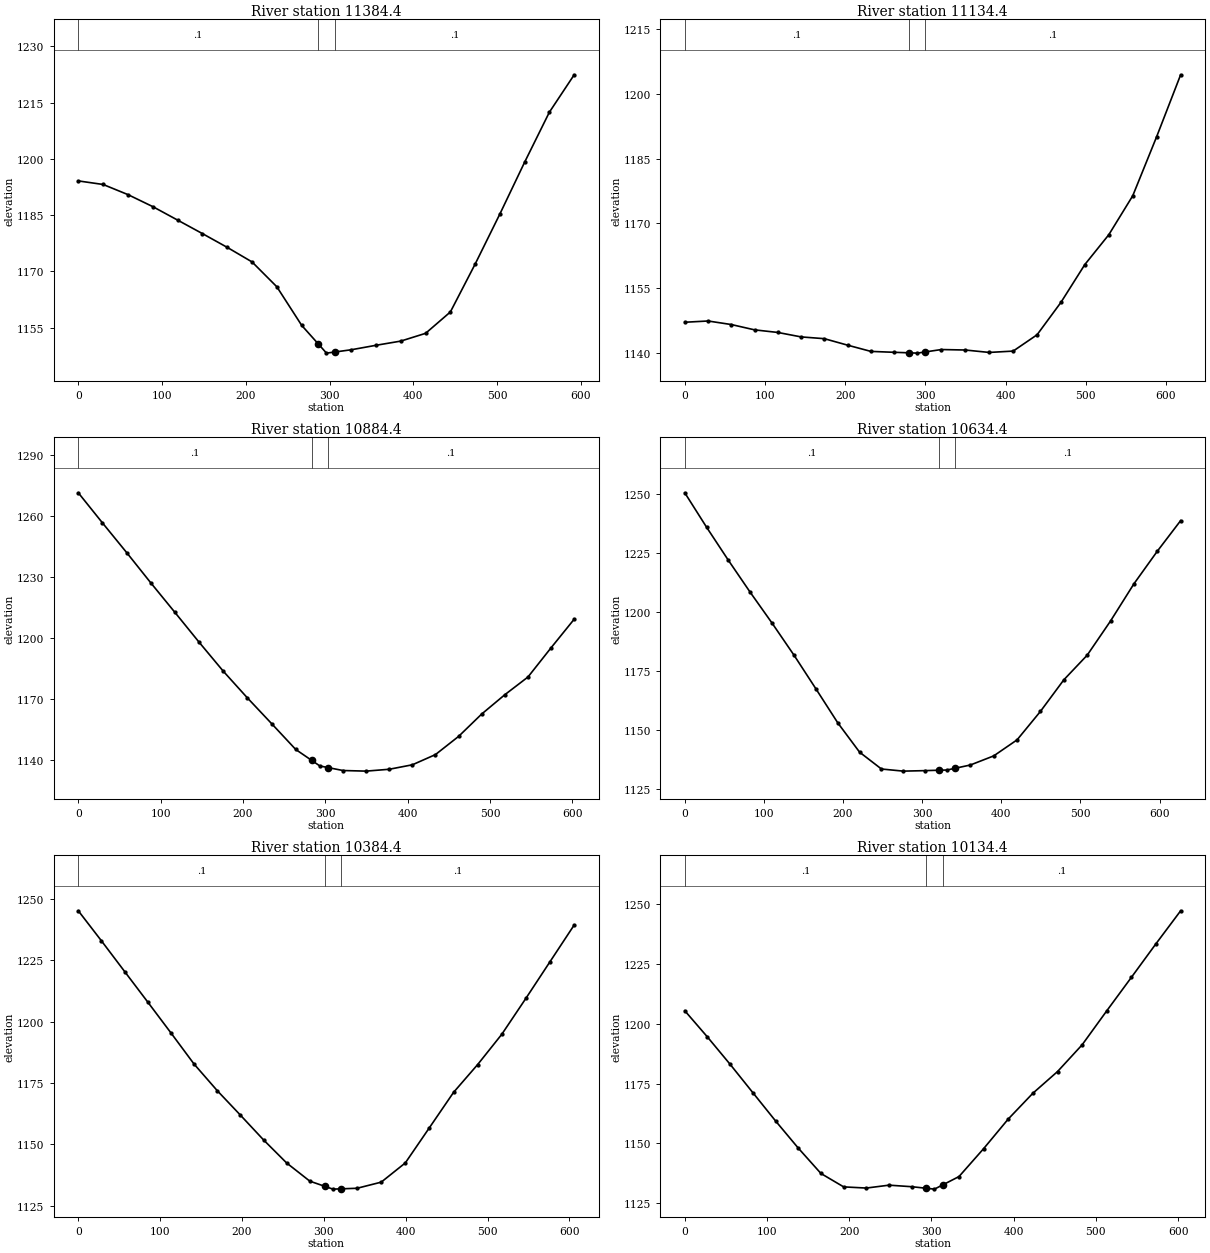
Type RM Length L Ch R = 1 ,11384.4,246.4,250,245.8
XS GIS Cut Line= 3
     1703177.523      418404.606     1703394.255      418606.642
     1703624.651      418792.005
#Sta/Elev= 23
       0 1194.13    29.6 1193.18    59.3 1190.47    88.9 1187.27   118.5 1183.68
   148.2 1180.07   177.8 1176.40   207.4 1172.52   237.0 1165.89   266.7 1155.59
   286.3 1150.69   296.3 1148.19   306.3 1148.49   325.9 1149.09   355.4 1150.28
   385.0 1151.40   414.6 1153.47   444.2 1159.17   473.7 1171.91   503.3 1185.30
   532.9 1199.14   562.4 1212.46   592.0 1222.43
#Mann= 3 , 0 , 0
       0     0.1       0   286.3   0.045       0   306.3     0.1       0
Bank Sta=286.3,306.3
Exp/Cntr=0.3,0.1

Type RM Length L Ch R = 1 ,11134.4,270,250,236
XS GIS Cut Line= 3
     1703021.847      418542.269     1703208.357      418764.377
     1703490.102      418932.560
#Sta/Elev= 24
       0 1147.15    29.0 1147.44    58.0 1146.62    87.0 1145.39   116.0 1144.79
   145.0 1143.76   174.0 1143.35   203.0 1141.85   232.0 1140.41   261.0 1140.20
     280 1140.08   290.0 1140.01     300 1140.29   319.9 1140.84   349.7 1140.73
   379.5 1140.17   409.4 1140.48   439.2 1144.25   469.0 1151.75   498.8 1160.50
   528.7 1167.40   558.5 1176.39   588.3 1190.05   618.2 1204.36
#Mann= 3 , 0 , 0
       0     0.1       0     280   0.045       0     300     0.1       0
Bank Sta=280,300
Exp/Cntr=0.3,0.1

Type RM Length L Ch R = 1 ,10884.4,274.7,250,262.7
XS GIS Cut Line= 3
     1702873.257      418984.969     1703165.914      419006.250
     1703474.782      419002.162
#Sta/Elev= 24
       0 1271.34    29.3 1256.54    58.7 1241.92    88.0 1227.02   117.4 1212.43
   146.7 1197.78   176.1 1183.49   205.4 1170.34   234.7 1157.73   264.1 1144.96
   283.4 1139.61   293.4 1136.84   303.4 1136.04   321.5 1134.60   349.6 1134.30
   377.7 1135.22   405.8 1137.42   433.8 1142.44   461.9 1151.39   490.0 1162.42
   518.1 1171.93   546.2 1180.65   574.2 1195.01   602.3 1209.10
#Mann= 3 , 0 , 0
       0     0.1       0   283.4   0.045       0   303.4     0.1       0
Bank Sta=283.4,303.4
Exp/Cntr=0.3,0.1

Type RM Length L Ch R = 1 ,10634.4,216.1,250,239
XS GIS Cut Line= 3
     1702875.266      419149.702     1703199.162      419219.523
     1703442.241      419387.186
#Sta/Elev= 25
       0 1250.44    27.6 1235.81    55.2 1221.76    82.8 1208.19   110.4 1195.12
   138.1 1181.53   165.7 1167.30   193.3 1152.88   220.9 1140.43   248.5 1133.29
   276.1 1132.39   303.7 1132.60   321.3 1132.77   331.3 1132.86   341.3 1133.58
   360.9 1134.99   390.4 1138.85   419.9 1145.65   449.4 1157.71   479.0 1171.12
   508.5 1181.56   538.0 1196.06   567.6 1211.85   597.1 1225.66   626.6 1238.64
#Mann= 3 , 0 , 0
       0     0.1       0   321.3   0.045       0   341.3     0.1       0
Bank Sta=321.3,341.3
Exp/Cntr=0.3,0.1

Type RM Length L Ch R = 1 ,10384.4,264.1,250,232.3
XS GIS Cut Line= 3
     1702835.864      419316.216     1703128.719      419421.028
     1703413.504      419496.609
#Sta/Elev= 24
       0 1245.05    28.3 1232.81    56.6 1220.34    84.8 1207.94   113.1 1195.40
   141.4 1182.70   169.7 1171.88   197.9 1161.96   226.2 1151.87   254.5 1142.46
   282.8 1135.06     301 1132.97   311.0 1131.82     321 1131.94   340.5 1132.17
   370.0 1134.66   399.4 1142.47   428.9 1156.82   458.4 1171.20   487.8 1182.50
   517.3 1194.82   546.8 1209.47   576.2 1224.35   605.7 1239.26
#Mann= 3 , 0 , 0
       0     0.1       0     301   0.045       0     321     0.1       0
Bank Sta=301,321
Exp/Cntr=0.3,0.1

Type RM Length L Ch R = 1 ,10134.4,239,250,259.1
XS GIS Cut Line= 3
     1702832.747      419722.815     1703127.047      419648.450
     1703414.784      419565.639
#Sta/Elev= 24
       0 1205.49    27.6 1194.49    55.2 1183.05    82.8 1171.20   110.4 1159.38
   138.0 1148.02   165.6 1137.39   193.2 1131.79   220.8 1131.30   248.4 1132.51
   276.0 1131.86   293.5 1131.22   303.6 1130.85   313.5 1132.59   333.5 1136.12
   363.4 1147.78   393.4 1160.20   423.3 1170.97   453.3 1180.05   483.2 1191.23
   513.1 1205.43   543.1 1219.46   573.0 1233.53   603.0 1247.31
#Mann= 3 , 0 , 0
       0     0.1       0   293.5   0.045       0   313.5     0.1       0
Bank Sta=293.5,313.5
Exp/Cntr=0.3,0.1

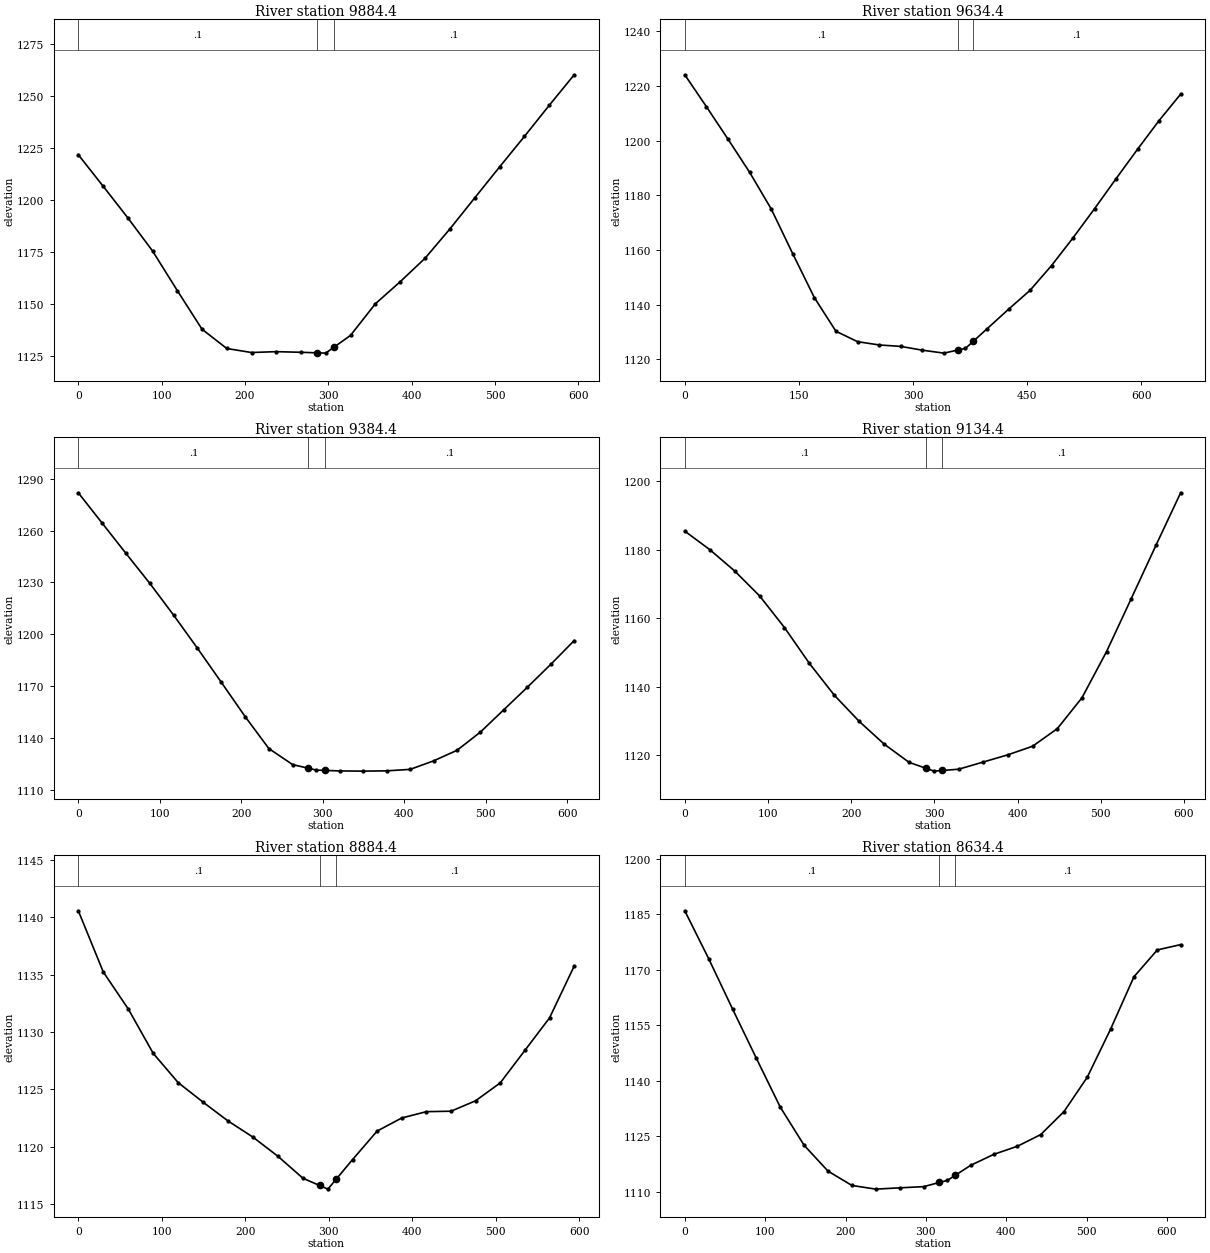
Type RM Length L Ch R = 1 ,9884.4,238.6,250,268.6
XS GIS Cut Line= 3
     1702822.061      419837.685     1703114.000      419891.461
     1703410.980      419916.289
#Sta/Elev= 23
       0 1221.67    29.7 1206.60    59.4 1191.33    89.1 1175.40   118.7 1156.40
   148.4 1137.79   178.1 1128.52   207.8 1126.58   237.5 1127.00   267.2 1126.69
   286.8 1126.43   296.8 1126.29   306.8 1129.16   326.6 1134.83   356.4 1150.03
   386.3 1160.67   416.1 1171.96   445.9 1186.06   475.7 1201.00   505.5 1215.87
   535.3 1230.55   565.1 1245.52   594.9 1260.13
#Mann= 3 , 0 , 0
       0     0.1       0   286.8   0.045       0   306.8     0.1       0
Bank Sta=286.8,306.8
Exp/Cntr=0.3,0.1

Type RM Length L Ch R = 1 ,9634.4,258.2,250,236.9
XS GIS Cut Line= 3
     1702804.976      419902.810     1703091.067      420135.897
     1703284.350      420342.263
#Sta/Elev= 26
       0 1224.12    28.4 1212.47    56.8 1200.58    85.2 1188.46   113.6 1175.04
   141.9 1158.66   170.3 1142.59   198.7 1130.28   227.1 1126.47   255.5 1125.27
   283.9 1124.74   312.2 1123.36   340.6 1122.28     359 1123.41   369.0 1124.02
     379 1126.55   397.3 1131.18   425.6 1138.34   453.8 1145.24   482.1 1154.32
   510.4 1164.48   538.7 1175.15   566.9 1186.10   595.2 1196.90   623.5 1207.39
   651.8 1217.04
#Mann= 3 , 0 , 0
       0     0.1       0     359   0.045       0     379     0.1       0
Bank Sta=359,379
Exp/Cntr=0.3,0.1

Type RM Length L Ch R = 1 ,9384.4,257.3,250,235.4
XS GIS Cut Line= 3
     1702670.143      420181.746     1702953.230      420254.325
     1703226.771      420412.799
#Sta/Elev= 24
       0 1281.83    29.2 1264.34    58.4 1246.83    87.7 1229.49   116.9 1211.12
   146.1 1192.01   175.4 1172.31   204.6 1152.49   233.8 1133.95   263.0 1124.68
   282.2 1122.59   292.2 1121.50   302.2 1121.33   321.0 1121.02   349.7 1120.91
   378.5 1121.07   407.2 1121.93   435.9 1126.84   464.7 1132.96   493.4 1143.50
   522.2 1156.46   550.9 1169.38   579.6 1182.60   608.4 1196.38
#Mann= 3 , 0 , 0
       0     0.1       0   282.2   0.045       0   302.2     0.1       0
Bank Sta=282.2,302.2
Exp/Cntr=0.3,0.1

Type RM Length L Ch R = 1 ,9134.4,238.4,250,257.9
XS GIS Cut Line= 3
     1702616.888      420517.125     1702915.759      420496.492
     1703211.964      420483.673
#Sta/Elev= 23
       0 1185.47    30.0 1180.06    59.9 1173.83    89.9 1166.53   119.8 1157.27
   149.8 1146.77   179.8 1137.45   209.7 1129.80   239.7 1123.16   269.6 1117.82
   289.6 1116.11   299.6 1115.25   309.6 1115.44   329.2 1115.81   358.9 1117.92
   388.5 1120.03   418.2 1122.54   447.8 1127.67   477.5 1136.71   507.1 1150.25
   536.8 1165.76   566.4 1181.30   596.1 1196.68
#Mann= 3 , 0 , 0
       0     0.1       0   289.6   0.045       0   309.6     0.1       0
Bank Sta=289.6,309.6
Exp/Cntr=0.3,0.1

Type RM Length L Ch R = 1 ,8884.4,246,250,246.1
XS GIS Cut Line= 3
     1702599.990      420633.140     1702878.978      420740.335
     1703161.317      420825.981
#Sta/Elev= 23
       0 1140.55    29.9 1135.22    59.8 1132.00    89.7 1128.13   119.6 1125.58
   149.4 1123.88   179.3 1122.24   209.2 1120.83   239.1 1119.16   269.0 1117.25
   288.9 1116.62   298.9 1116.30   308.9 1117.17   328.4 1118.87   357.9 1121.36
   387.4 1122.50   416.9 1123.05   446.4 1123.09   475.9 1124.00   505.4 1125.56
   534.9 1128.39   564.4 1131.22   593.9 1135.73
#Mann= 3 , 0 , 0
       0     0.1       0   288.9   0.045       0   308.9     0.1       0
Bank Sta=288.9,308.9
Exp/Cntr=0.3,0.1

Type RM Length L Ch R = 1 ,8634.4,241.5,250,264
XS GIS Cut Line= 3
     1702542.836      420861.656     1702847.591      420979.630
     1703133.891      421026.899
#Sta/Elev= 24
       0 1185.96    29.7 1173.03    59.4 1159.43    89.1 1146.06   118.8 1132.88
   148.5 1122.56   178.2 1115.58   208.0 1111.70   237.7 1110.71   267.4 1111.06
   297.1 1111.38   316.8 1112.51   326.8 1113.08   336.8 1114.48   355.8 1117.15
   384.8 1120.14   413.8 1122.29   442.9 1125.46   471.9 1131.68   500.9 1141.00
   529.9 1153.99   558.9 1168.12   588.0 1175.39   617.0 1176.82
#Mann= 3 , 0 , 0
       0     0.1       0   316.8   0.045       0   336.8     0.1       0
Bank Sta=316.8,336.8
Exp/Cntr=0.3,0.1

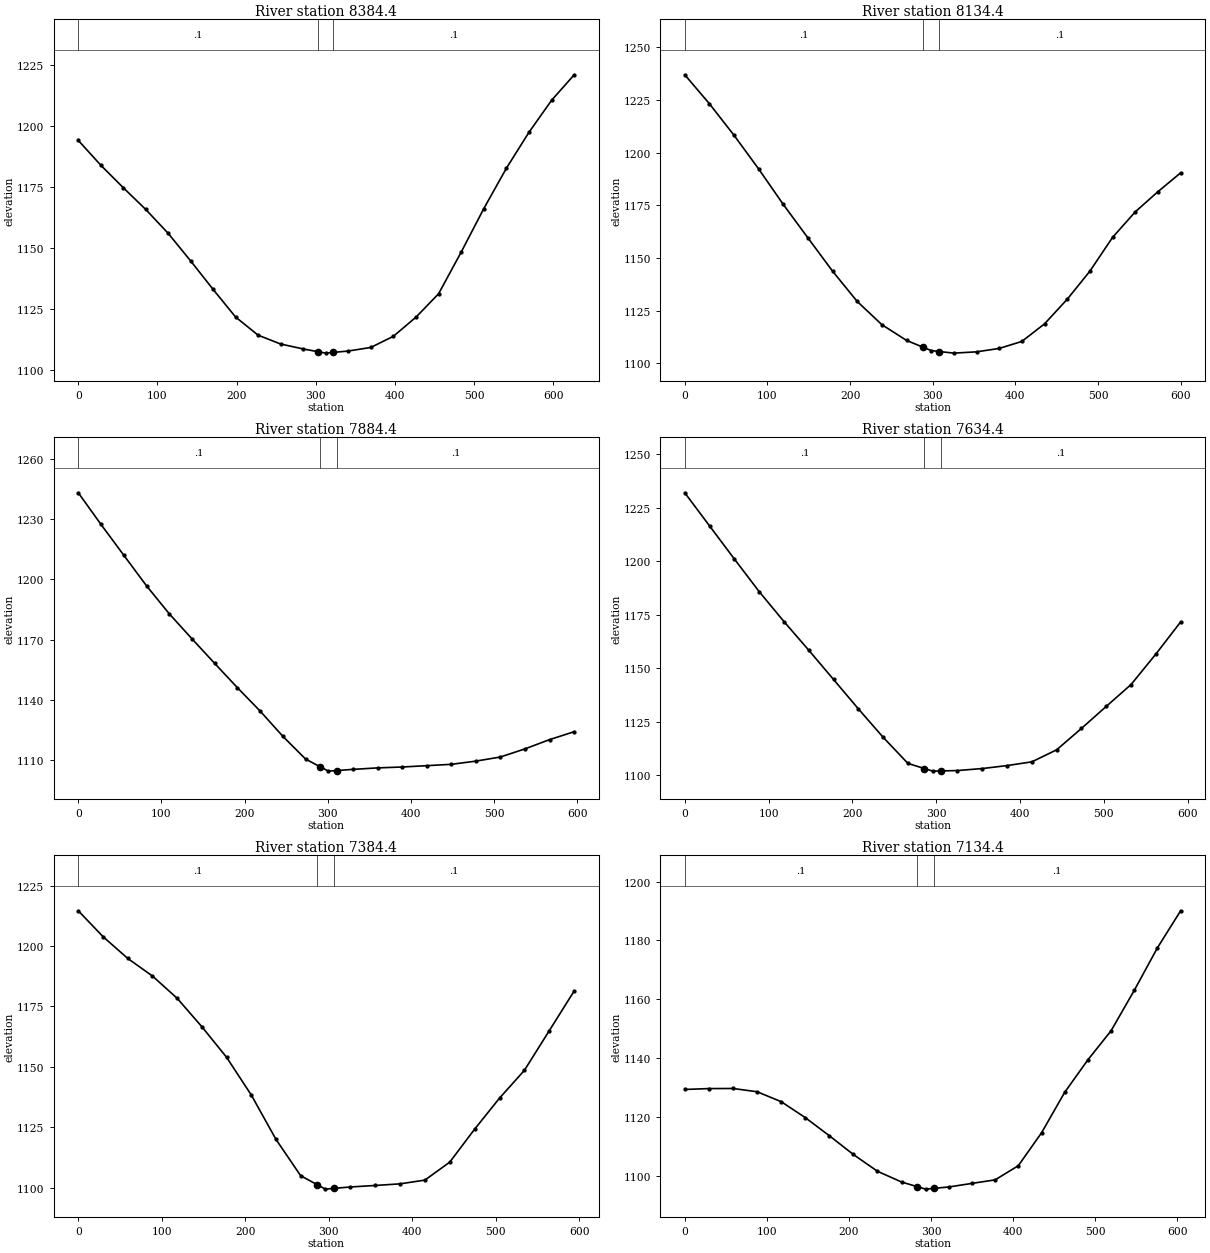
Type RM Length L Ch R = 1 ,8384.4,253.7,250,245.9
XS GIS Cut Line= 3
     1702505.784      420916.792     1702706.417      421156.099
     1702916.455      421389.687
#Sta/Elev= 25
       0 1193.98    28.4 1183.84    56.8 1174.64    85.2 1165.74   113.6 1155.93
   142.0 1144.64   170.3 1133.03   198.7 1121.72   227.1 1114.31   255.5 1110.70
   283.9 1108.68   302.3 1107.57   312.3 1106.96   322.3 1107.26   340.8 1107.81
   369.4 1109.28   398.0 1113.84   426.5 1121.66   455.1 1131.23   483.6 1148.25
   512.2 1166.07   540.7 1182.56   569.3 1197.31   597.9 1210.41   626.4 1220.83
#Mann= 3 , 0 , 0
       0     0.1       0   302.3   0.045       0   322.3     0.1       0
Bank Sta=302.3,322.3
Exp/Cntr=0.3,0.1

Type RM Length L Ch R = 1 ,8134.4,245.9,250,256
XS GIS Cut Line= 3
     1702347.153      421156.594     1702584.182      421337.330
     1702805.669      421542.445
#Sta/Elev= 24
       0 1236.87    29.8 1223.14    59.6 1208.17    89.4 1192.18   119.2 1175.34
   149.0 1159.47   178.8 1143.70   208.6 1129.33   238.5 1118.29   268.3 1110.83
   288.1 1107.63   298.1 1106.01   308.1 1105.56   325.5 1104.79   353.0 1105.40
   380.4 1107.01   407.8 1110.33   435.3 1118.68   462.7 1130.32   490.2 1143.69
   517.6 1159.69   545.1 1171.84   572.5 1181.40   600.0 1190.34
#Mann= 3 , 0 , 0
       0     0.1       0   288.1   0.045       0   308.1     0.1       0
Bank Sta=288.1,308.1
Exp/Cntr=0.3,0.1

Type RM Length L Ch R = 1 ,7884.4,250.9,250,243.6
XS GIS Cut Line= 3
     1702238.210      421332.492     1702453.176      421542.691
     1702617.186      421788.674
#Sta/Elev= 24
       0 1243.13    27.3 1227.35    54.7 1212.01    82.0 1196.78   109.3 1182.86
   136.7 1170.34   164.0 1158.09   191.3 1146.00   218.7 1134.31   246.0 1121.74
   273.3 1110.42   290.7 1106.60   300.7 1104.40   310.7 1104.69   330.2 1105.27
   359.8 1106.01   389.4 1106.45   418.9 1107.12   448.5 1107.79   478.0 1109.38
   507.6 1111.44   537.2 1115.50   566.7 1120.10   596.3 1124.05
#Mann= 3 , 0 , 0
       0     0.1       0   290.7   0.045       0   310.7     0.1       0
Bank Sta=290.7,310.7
Exp/Cntr=0.3,0.1

Type RM Length L Ch R = 1 ,7634.4,242.6,250,252.8
XS GIS Cut Line= 3
     1702047.218      421507.386     1702266.055      421706.330
     1702484.891      421905.274
#Sta/Elev= 23
       0 1231.94    29.6 1216.44    59.2 1200.98    88.7 1185.79   118.3 1171.78
   147.9 1158.39   177.4 1144.73   207.0 1131.00   236.6 1117.70   266.2 1105.48
   285.8 1103.10   295.8 1101.88   305.8 1101.97   325.3 1102.15   354.9 1103.09
   384.5 1104.47   414.0 1106.22   443.6 1111.84   473.2 1121.83   502.8 1132.14
   532.4 1142.36   561.9 1156.56   591.5 1171.59
#Mann= 3 , 0 , 0
       0     0.1       0   285.8   0.045       0   305.8     0.1       0
Bank Sta=285.8,305.8
Exp/Cntr=0.3,0.1

Type RM Length L Ch R = 1 ,7384.4,266.7,250,235.3
XS GIS Cut Line= 3
     1701929.088      421621.305     1702082.206      421874.564
     1702276.734      422100.519
#Sta/Elev= 23
       0 1214.57    29.6 1203.88    59.2 1194.87    88.8 1187.60   118.4 1178.38
   148.0 1166.62   177.6 1153.98   207.2 1138.38   236.8 1120.00   266.4 1104.96
   285.9 1101.30   296.0 1099.41   305.9 1099.71   325.8 1100.30   355.6 1100.92
   385.4 1101.59   415.2 1103.14   445.0 1110.57   474.8 1124.20   504.7 1137.08
   534.5 1148.58   564.3 1164.98   594.1 1181.39
#Mann= 3 , 0 , 0
       0     0.1       0   285.9   0.045       0   305.9     0.1       0
Bank Sta=285.9,305.9
Exp/Cntr=0.3,0.1

Type RM Length L Ch R = 1 ,7134.4,247.5,250,251.6
XS GIS Cut Line= 3
     1701663.361      421966.624     1701939.240      422066.496
     1702236.129      422158.623
#Sta/Elev= 24
       0 1129.35    29.3 1129.65    58.7 1129.68    88.0 1128.58   117.4 1125.21
   146.7 1119.81   176.0 1113.66   205.4 1107.26   234.7 1101.57   264.1 1097.91
   283.4 1096.32   293.4 1095.49   303.4 1095.75   321.7 1096.22   349.9 1097.44
   378.2 1098.64   406.4 1103.45   434.7 1114.62   463.0 1128.41   491.2 1139.42
   519.5 1149.31   547.7 1163.02   576.0 1177.51   604.2 1190.04
#Mann= 3 , 0 , 0
       0     0.1       0   283.4   0.045       0   303.4     0.1       0
Bank Sta=283.4,303.4
Exp/Cntr=0.3,0.1

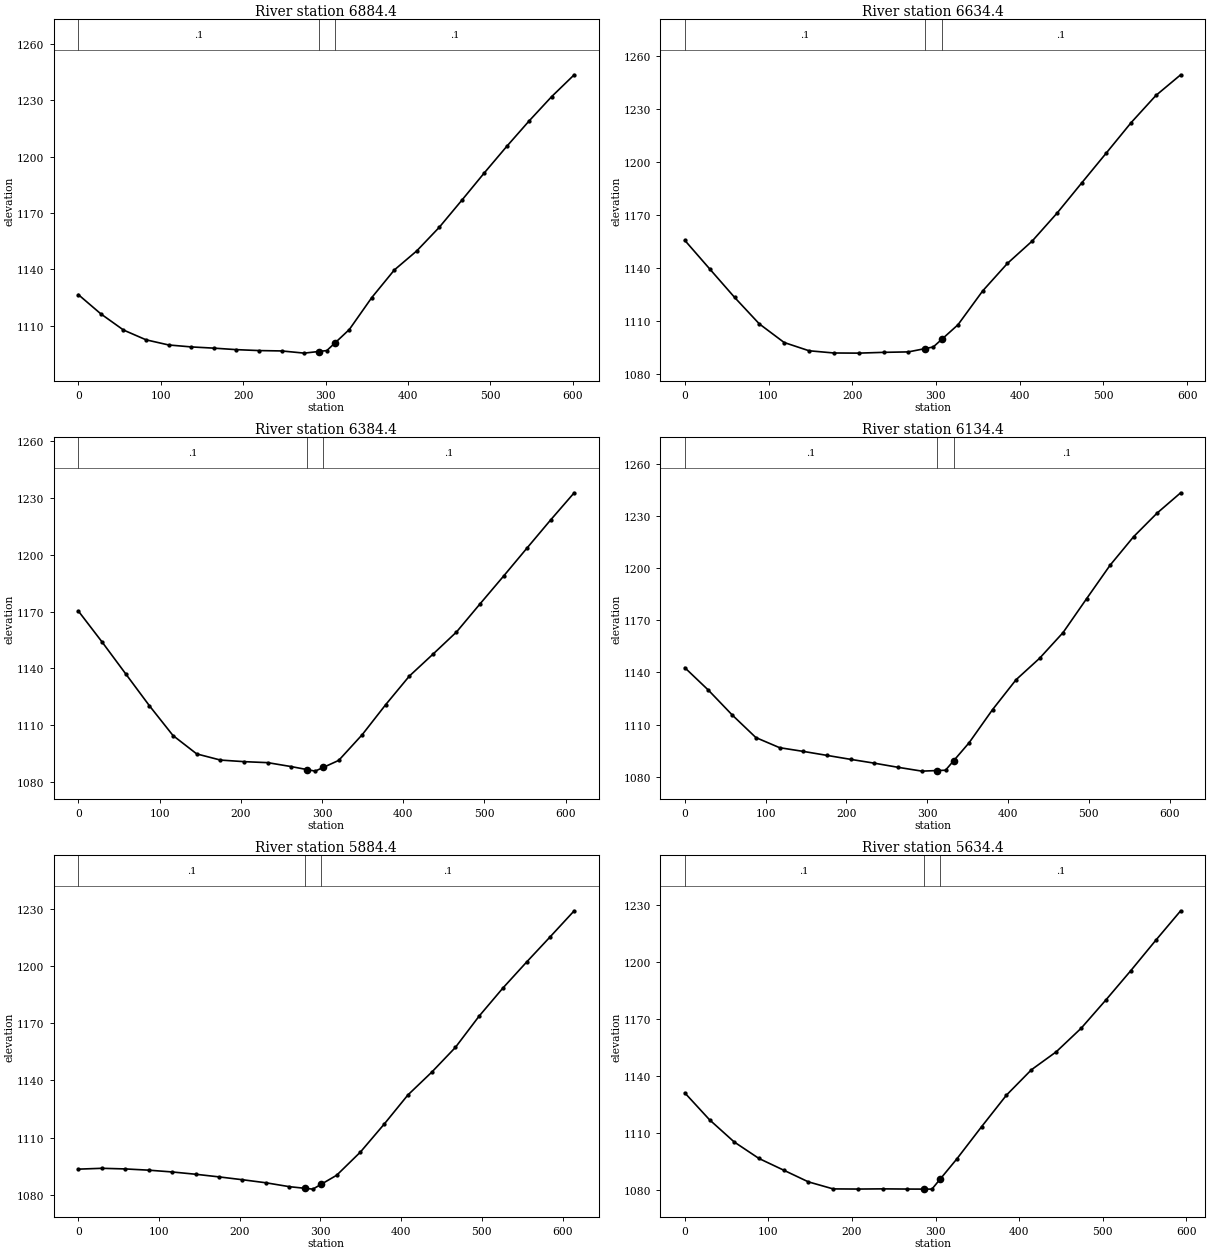
Type RM Length L Ch R = 1 ,6884.4,255.5,250,242.3
XS GIS Cut Line= 3
     1701630.023      422180.619     1701903.738      422307.018
     1702178.225      422428.425
#Sta/Elev= 25
       0 1126.63    27.4 1116.37    54.8 1107.81    82.2 1102.60   109.6 1099.87
   137.0 1098.83   164.4 1098.18   191.9 1097.38   219.3 1096.89   246.7 1096.69
   274.1 1095.53   291.5 1096.39   301.5 1096.89   311.5 1100.99   328.8 1108.08
   356.1 1125.10   383.4 1139.73   410.6 1149.87   437.9 1162.41   465.2 1176.75
   492.5 1191.30   519.8 1205.44   547.1 1219.04   574.3 1231.90   601.6 1243.48
#Mann= 3 , 0 , 0
       0     0.1       0   291.5   0.045       0   311.5     0.1       0
Bank Sta=291.5,311.5
Exp/Cntr=0.3,0.1

Type RM Length L Ch R = 1 ,6634.4,237.4,250,253.3
XS GIS Cut Line= 3
     1701571.723      422490.812     1701863.448      422545.307
     1702157.392      422576.286
#Sta/Elev= 23
       0 1155.66    29.7 1139.49    59.4 1123.39    89.0 1108.34   118.7 1097.79
   148.4 1093.12   178.1 1091.86   207.7 1091.78   237.4 1092.22   267.1 1092.48
   286.8 1094.32   296.8 1095.26   306.8 1099.52   326.3 1107.83   355.9 1127.04
   385.4 1142.60   415.0 1155.26   444.6 1171.02   474.1 1188.15   503.7 1205.22
   533.2 1222.33   562.8 1237.72   592.3 1249.39
#Mann= 3 , 0 , 0
       0     0.1       0   286.8   0.045       0   306.8     0.1       0
Bank Sta=286.8,306.8
Exp/Cntr=0.3,0.1

Type RM Length L Ch R = 1 ,6384.4,261.4,250,246.6
XS GIS Cut Line= 3
     1701518.177      422589.344     1701755.753      422758.389
     1702060.063      422853.957
#Sta/Elev= 24
       0 1170.28    29.2 1153.98    58.3 1137.20    87.5 1120.40   116.6 1104.69
   145.8 1095.02   175.0 1091.78   204.1 1090.95   233.3 1090.42   262.4 1088.33
   281.6 1086.77   291.6 1085.96   301.6 1087.91   320.6 1091.61   349.6 1105.18
   378.6 1121.04   407.6 1136.02   436.6 1147.52   465.6 1159.21   494.6 1174.02
   523.6 1188.65   552.6 1203.50   581.6 1218.25   610.5 1232.50
#Mann= 3 , 0 , 0
       0     0.1       0   281.6   0.045       0   301.6     0.1       0
Bank Sta=281.6,301.6
Exp/Cntr=0.3,0.1

Type RM Length L Ch R = 1 ,6134.4,259.8,250,249.6
XS GIS Cut Line= 3
     1701435.962      422968.643     1701758.607      422975.684
     1702046.485      423018.110
#Sta/Elev= 24
       0 1142.74    29.3 1129.79    58.7 1115.56    88.0 1102.58   117.4 1096.77
   146.7 1094.64   176.0 1092.35   205.4 1090.06   234.7 1087.87   264.0 1085.50
   293.4 1083.31   312.7 1083.65   322.7 1083.83   332.7 1089.24   351.8 1099.56
   380.9 1118.64   410.0 1135.81   439.1 1148.13   468.2 1162.91   497.3 1182.36
   526.4 1201.61   555.5 1217.98   584.6 1231.56   613.7 1243.19
#Mann= 3 , 0 , 0
       0     0.1       0   312.7   0.045       0   332.7     0.1       0
Bank Sta=312.7,332.7
Exp/Cntr=0.3,0.1

Type RM Length L Ch R = 1 ,5884.4,247.6,250,239.9
XS GIS Cut Line= 3
     1701400.957      423303.286     1701672.969      423200.908
     1701994.988      423234.188
#Sta/Elev= 24
       0 1093.46    29.1 1093.90    58.1 1093.57    87.2 1092.92   116.3 1091.98
   145.3 1090.78   174.4 1089.39   203.4 1087.90   232.5 1086.30   261.6 1084.25
   280.6 1083.41   290.6 1082.97   300.6 1085.44   320.1 1090.25   349.5 1102.41
   378.9 1117.04   408.4 1132.40   437.8 1144.30   467.2 1157.33   496.6 1173.75
   526.1 1188.50   555.5 1202.16   584.9 1215.49   614.4 1229.03
#Mann= 3 , 0 , 0
       0     0.1       0   280.6   0.045       0   300.6     0.1       0
Bank Sta=280.6,300.6
Exp/Cntr=0.3,0.1

Type RM Length L Ch R = 1 ,5634.4,235.7,250,262.8
XS GIS Cut Line= 3
     1701444.790      423521.510     1701729.772      423443.045
     1702019.254      423374.505
#Sta/Elev= 23
       0 1131.13    29.6 1116.96    59.1 1105.28    88.7 1096.59   118.2 1090.45
   147.8 1084.28   177.4 1080.57   206.9 1080.49   236.5 1080.59   266.0 1080.49
   285.6 1080.46   295.6 1080.45   305.6 1085.79   325.3 1096.30   355.1 1113.37
   384.8 1129.96   414.6 1143.29   444.3 1152.75   474.1 1165.15   503.8 1180.10
   533.6 1195.54   563.3 1211.43   593.1 1226.98
#Mann= 3 , 0 , 0
       0     0.1       0   285.6   0.045       0   305.6     0.1       0
Bank Sta=285.6,305.6
Exp/Cntr=0.3,0.1

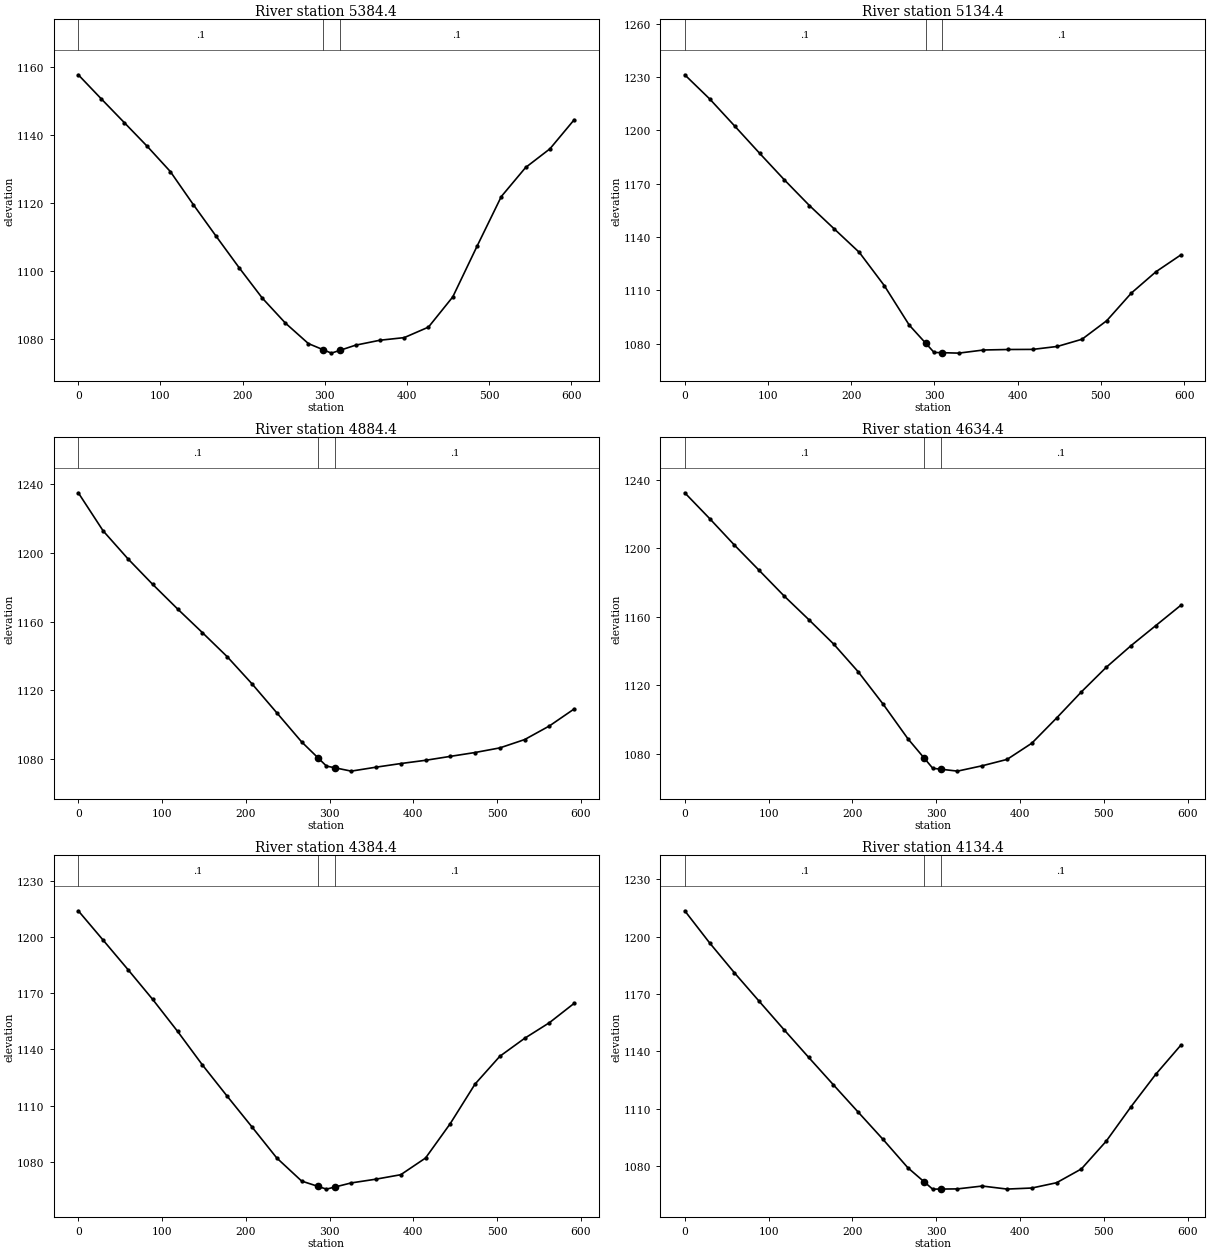
Type RM Length L Ch R = 1 ,5384.4,263.6,250,236.2
XS GIS Cut Line= 3
     1701446.068      423592.769     1701740.892      423682.126
     1702023.699      423768.301
#Sta/Elev= 24
       0 1157.72    28.0 1150.64    56.0 1143.66    84.0 1136.67   112.0 1129.28
   140.0 1119.56   168.0 1110.18   196.0 1100.93   224.0 1092.06   252.1 1084.72
   280.1 1078.69   298.1 1076.88   308.1 1075.88   318.1 1076.67   337.6 1078.22
   367.2 1079.67   396.8 1080.44   426.3 1083.53   455.9 1092.41   485.4 1107.29
   515.0 1121.93   544.6 1130.47   574.2 1135.96   603.7 1144.50
#Mann= 3 , 0 , 0
       0     0.1       0   298.1   0.045       0   318.1     0.1       0
Bank Sta=298.1,318.1
Exp/Cntr=0.3,0.1

Type RM Length L Ch R = 1 ,5134.4,237.5,250,260.6
XS GIS Cut Line= 3
     1701445.910      423982.797     1701735.977      423907.734
     1702023.506      423836.651
#Sta/Elev= 23
       0 1231.22    30.0 1217.62    59.9 1202.46    89.9 1187.11   119.8 1172.09
   149.8 1157.70   179.8 1144.48   209.7 1131.38   239.7 1112.71   269.7 1090.49
   289.6 1080.25   299.6 1075.10   309.6 1074.98   329.2 1074.73   358.9 1076.49
   388.5 1076.77   418.1 1076.83   447.7 1078.49   477.3 1082.54   507.0 1092.96
   536.6 1108.51   566.2 1120.51   595.8 1129.87
#Mann= 3 , 0 , 0
       0     0.1       0   289.6   0.045       0   309.6     0.1       0
Bank Sta=289.6,309.6
Exp/Cntr=0.3,0.1

Type RM Length L Ch R = 1 ,4884.4,240.6,250,260.4
XS GIS Cut Line= 3
     1701438.275      424084.856     1701726.088      424154.932
     1702016.565      424210.087
#Sta/Elev= 23
       0 1234.88    29.6 1212.76    59.2 1196.51    88.9 1181.56   118.5 1167.32
   148.1 1153.56   177.7 1139.56   207.4 1123.72   237.0 1106.87   266.6 1089.98
   286.2 1080.67   296.2 1075.92   306.2 1074.93   325.8 1072.98   355.4 1075.28
   384.9 1077.39   414.5 1079.28   444.0 1081.56   473.6 1083.81   503.2 1086.50
   532.8 1091.34   562.3 1099.25   591.9 1109.15
#Mann= 3 , 0 , 0
       0     0.1       0   286.2   0.045       0   306.2     0.1       0
Bank Sta=286.2,306.2
Exp/Cntr=0.3,0.1

Type RM Length L Ch R = 1 ,4634.4,249.5,250,249
XS GIS Cut Line= 3
     1701372.403      424207.668     1701614.871      424377.011
     1701857.339      424546.354
#Sta/Elev= 23
       0 1232.32    29.6 1217.31    59.2 1201.82    88.7 1187.06   118.3 1172.20
   147.9 1158.31   177.4 1144.14   207.0 1127.78   236.6 1108.95   266.2 1088.73
   285.8 1077.33   295.8 1071.51   305.8 1070.95   325.3 1069.85   354.9 1072.99
   384.5 1076.70   414.0 1086.16   443.6 1100.89   473.2 1116.16   502.8 1130.48
   532.4 1143.13   561.9 1154.83   591.5 1166.57
#Mann= 3 , 0 , 0
       0     0.1       0   285.8   0.045       0   305.8     0.1       0
Bank Sta=285.8,305.8
Exp/Cntr=0.3,0.1

Type RM Length L Ch R = 1 ,4384.4,242.8,250,257.8
XS GIS Cut Line= 3
     1701223.359      424402.255     1701463.816      424575.148
     1701711.502      424736.751
#Sta/Elev= 23
       0 1214.02    29.6 1198.37    59.2 1182.66    88.8 1166.68   118.5 1149.62
   148.1 1131.70   177.7 1114.98   207.3 1098.56   236.9 1081.98   266.6 1069.64
   286.2 1066.79   296.2 1065.34   306.2 1066.46   325.7 1068.65   355.3 1070.66
   384.9 1073.04   414.5 1081.96   444.0 1100.35   473.6 1121.48   503.2 1136.32
   532.8 1145.92   562.3 1154.24   591.9 1164.60
#Mann= 3 , 0 , 0
       0     0.1       0   286.2   0.045       0   306.2     0.1       0
Bank Sta=286.2,306.2
Exp/Cntr=0.3,0.1

Type RM Length L Ch R = 1 ,4134.4,253.5,250,244.6
XS GIS Cut Line= 3
     1701097.859      424509.967     1701280.571      424742.509
     1701466.134      424972.904
#Sta/Elev= 23
       0 1213.58    29.6 1196.79    59.2 1181.13    88.7 1166.22   118.3 1151.36
   147.9 1136.76   177.4 1122.39   207.0 1108.08   236.6 1093.81   266.2 1078.96
   285.7 1071.58   295.7 1067.79   305.7 1067.83   325.3 1067.91   354.9 1069.41
   384.5 1067.82   414.1 1068.37   443.6 1071.14   473.2 1078.37   502.8 1092.90
   532.4 1110.95   562.0 1127.99   591.6 1143.07
#Mann= 3 , 0 , 0
       0     0.1       0   285.7   0.045       0   305.7     0.1       0
Bank Sta=285.7,305.7
Exp/Cntr=0.3,0.1

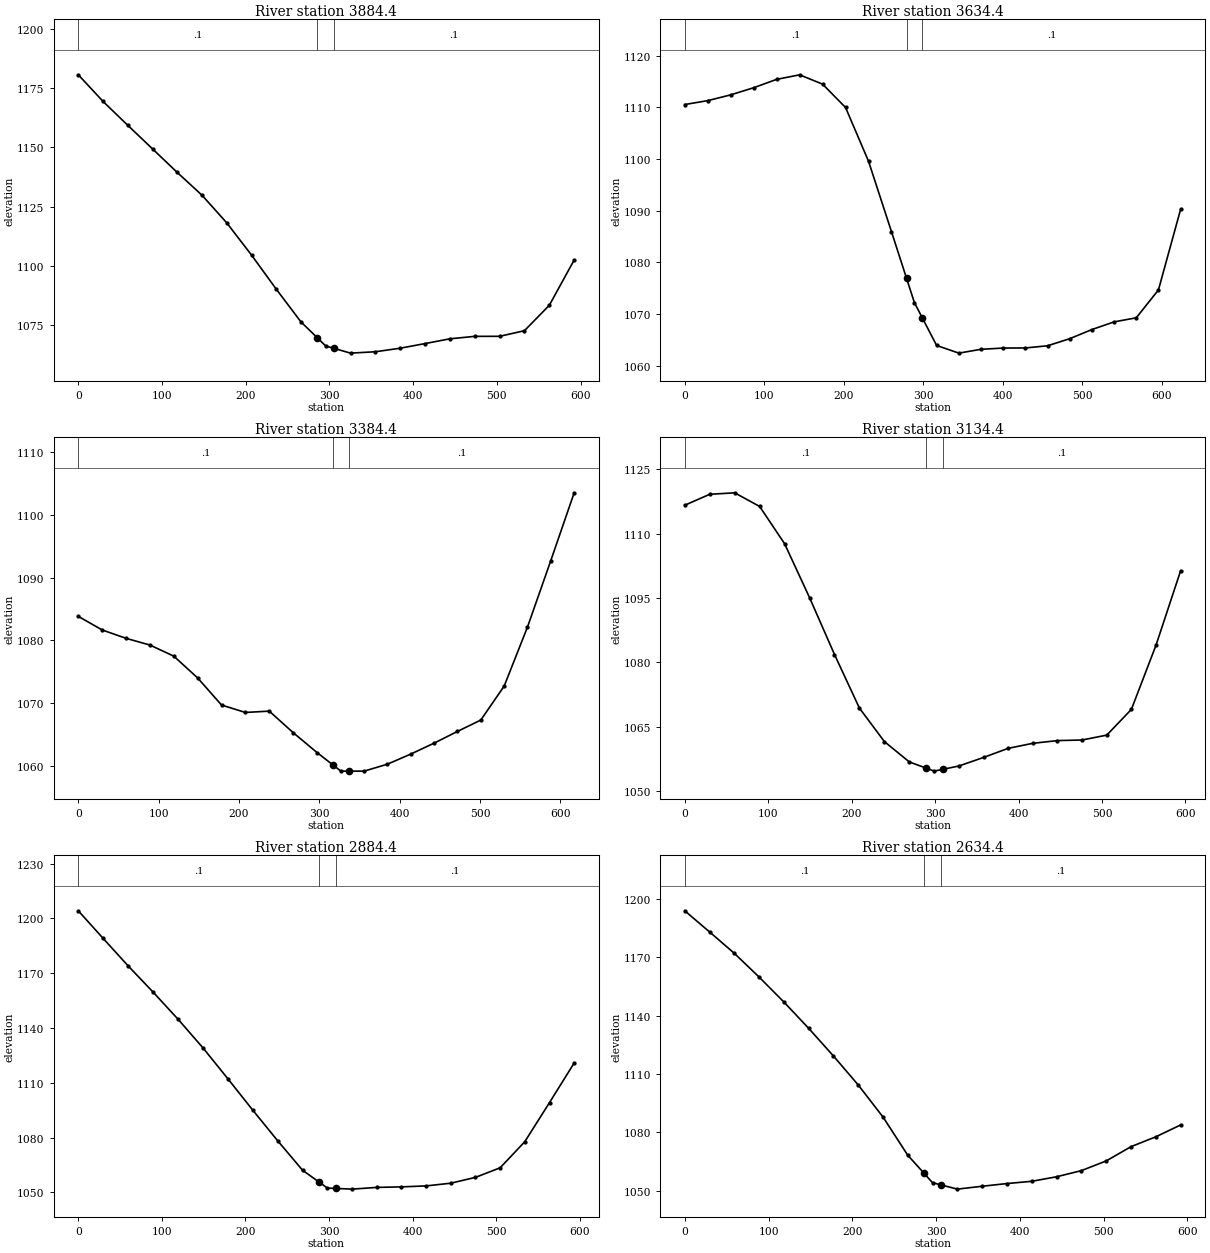
Type RM Length L Ch R = 1 ,3884.4,271.8,250,236.5
XS GIS Cut Line= 3
     1700894.246      424719.064     1701108.268      424922.892
     1701339.529      425109.033
#Sta/Elev= 23
       0 1180.72    29.6 1169.45    59.1 1159.37    88.7 1149.39   118.2 1139.44
   147.8 1129.80   177.3 1118.15   206.9 1104.52   236.4 1090.14   266.0 1076.26
   285.6 1069.52   295.6 1066.08   305.6 1065.06   325.2 1063.06   354.9 1063.64
   384.6 1065.14   414.3 1067.10   444.0 1069.12   473.7 1070.15   503.4 1070.17
   533.0 1072.54   562.7 1083.28   592.4 1102.42
#Mann= 3 , 0 , 0
       0     0.1       0   285.6   0.045       0   305.6     0.1       0
Bank Sta=285.6,305.6
Exp/Cntr=0.3,0.1

Type RM Length L Ch R = 1 ,3634.4,243.5,250,240.7
XS GIS Cut Line= 3
     1700688.080      425150.815     1700975.168      425118.916
     1701306.264      425168.742
#Sta/Elev= 25
       0 1110.54    28.9 1111.29    57.8 1112.41    86.7 1113.79   115.5 1115.40
   144.4 1116.28   173.3 1114.48   202.2 1109.97   231.1 1099.58   260.0 1085.95
   278.9 1076.96   288.8 1072.25   298.9 1069.26   316.8 1063.96   344.7 1062.48
   372.6 1063.22   400.5 1063.46   428.4 1063.48   456.3 1063.90   484.2 1065.27
   512.1 1067.04   540.0 1068.52   567.9 1069.31   595.8 1074.70   623.7 1090.28
#Mann= 3 , 0 , 0
       0     0.1       0   278.9   0.045       0   298.9     0.1       0
Bank Sta=278.9,298.9
Exp/Cntr=0.3,0.1

Type RM Length L Ch R = 1 ,3384.4,236.8,250,273.5
XS GIS Cut Line= 3
     1700720.493      425318.626     1701044.770      425358.049
     1701329.547      425301.719
#Sta/Elev= 24
       0 1083.81    29.7 1081.65    59.4 1080.32    89.1 1079.25   118.8 1077.48
   148.5 1074.01   178.2 1069.70   207.9 1068.52   237.6 1068.73   267.3 1065.31
   297.0 1062.14   316.7 1060.18   326.7 1059.18   336.7 1059.18   355.7 1059.18
   384.7 1060.29   413.8 1061.90   442.8 1063.64   471.8 1065.50   500.8 1067.31
   529.9 1072.71   558.9 1082.11   587.9 1092.68   617.0 1103.48
#Mann= 3 , 0 , 0
       0     0.1       0   316.7   0.045       0   336.7     0.1       0
Bank Sta=316.7,336.7
Exp/Cntr=0.3,0.1

Type RM Length L Ch R = 1 ,3134.4,256.4,250,240.1
XS GIS Cut Line= 3
     1700691.122      425379.077     1700930.285      425558.457
     1701145.498      425760.639
#Sta/Elev= 23
       0 1116.66    29.9 1119.21    59.8 1119.55    89.7 1116.37   119.6 1107.68
   149.5 1095.11   179.4 1081.84   209.3 1069.33   239.2 1061.53   269.1 1056.78
     289 1055.36   299.0 1054.64     309 1055.05   328.5 1055.84   358.0 1057.83
   387.5 1059.95   417.1 1061.13   446.6 1061.76   476.1 1061.90   505.7 1063.04
   535.2 1069.04   564.7 1084.01   594.2 1101.37
#Mann= 3 , 0 , 0
       0     0.1       0     289   0.045       0     309     0.1       0
Bank Sta=289,309
Exp/Cntr=0.3,0.1

Type RM Length L Ch R = 1 ,2884.4,244.6,250,256.2
XS GIS Cut Line= 3
     1700536.693      425663.805     1700813.982      425773.473
     1701089.532      425879.670
#Sta/Elev= 23
       0 1204.12    29.8 1188.98    59.6 1173.98    89.5 1159.62   119.3 1144.81
   149.1 1129.14   178.9 1112.25   208.7 1095.06   238.6 1078.25   268.4 1062.11
   288.2 1055.63   298.2 1052.35   308.2 1052.15   327.7 1051.77   357.2 1052.71
   386.8 1053.01   416.3 1053.53   445.8 1055.01   475.4 1058.21   504.9 1063.45
   534.4 1077.73   564.0 1099.15   593.5 1120.81
#Mann= 3 , 0 , 0
       0     0.1       0   288.2   0.045       0   308.2     0.1       0
Bank Sta=288.2,308.2
Exp/Cntr=0.3,0.1

Type RM Length L Ch R = 1 ,2634.4,253.2,250,246.2
XS GIS Cut Line= 3
     1700421.139      425811.007     1700668.816      425972.534
     1700908.802      426145.920
#Sta/Elev= 23
       0 1193.97    29.6 1183.10    59.1 1172.10    88.7 1159.88   118.3 1147.02
   147.8 1133.52   177.4 1119.26   207.0 1104.33   236.6 1087.82   266.1 1068.18
   285.7 1058.80   295.7 1054.02   305.7 1052.91   325.3 1050.72   354.9 1052.20
   384.5 1053.59   414.1 1054.75   443.7 1057.08   473.3 1060.24   502.9 1065.22
   532.6 1072.58   562.2 1077.65   591.8 1083.76
#Mann= 3 , 0 , 0
       0     0.1       0   285.7   0.045       0   305.7     0.1       0
Bank Sta=285.7,305.7
Exp/Cntr=0.3,0.1