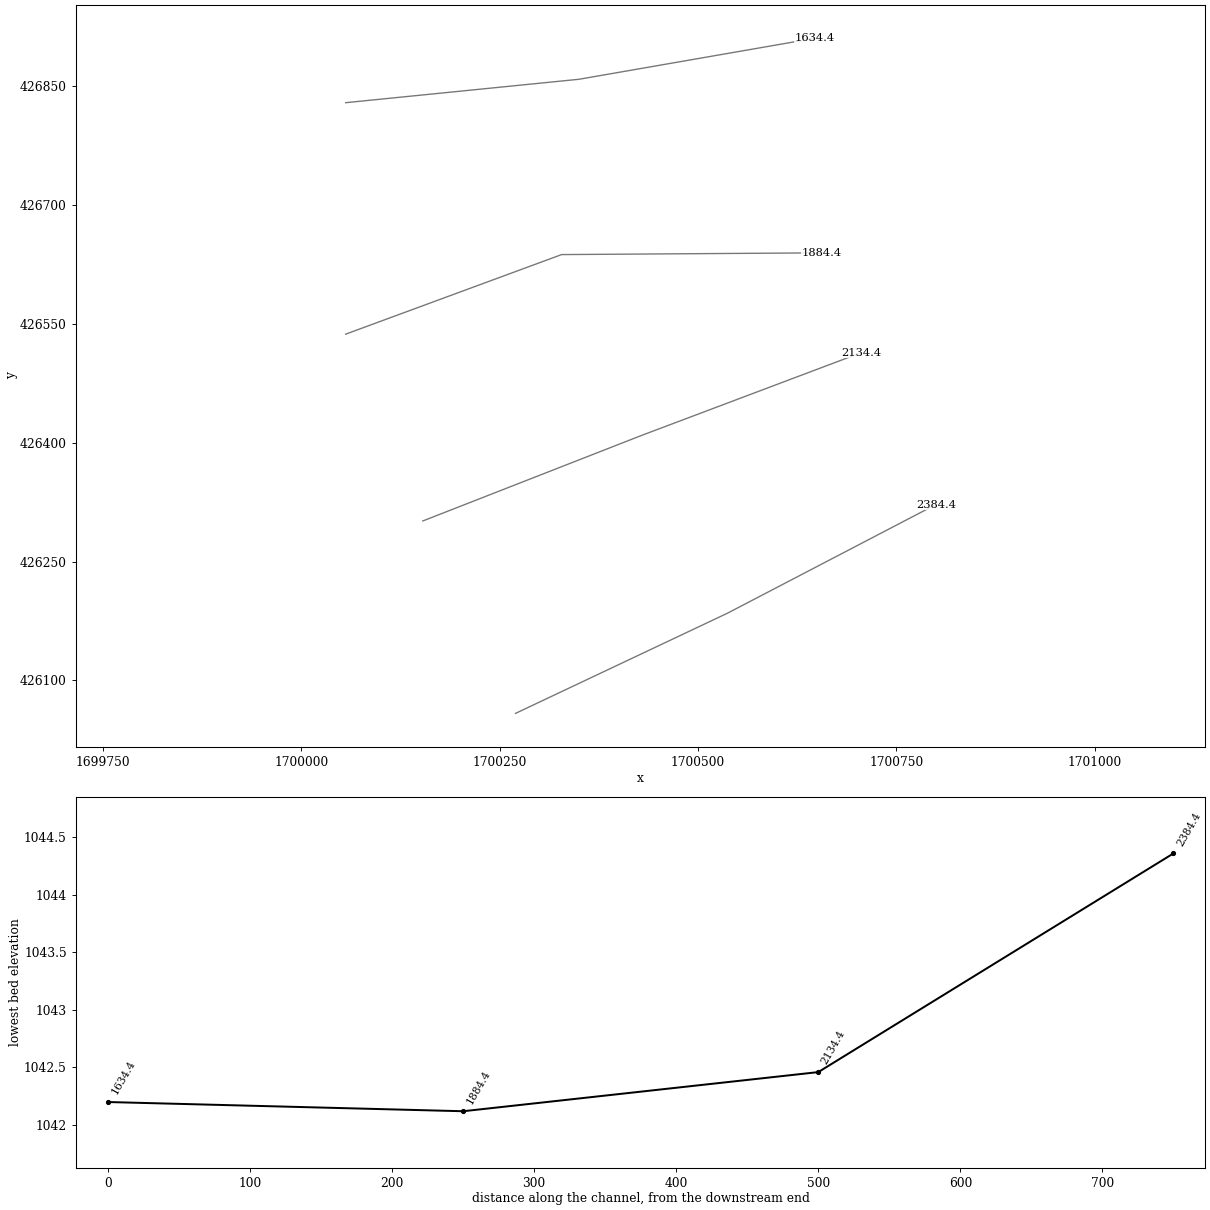
HEC-RAS study RUSHRN2.prj: RUSHRN2

--- RUSHRN2.g01 (geometry) --- (continued)

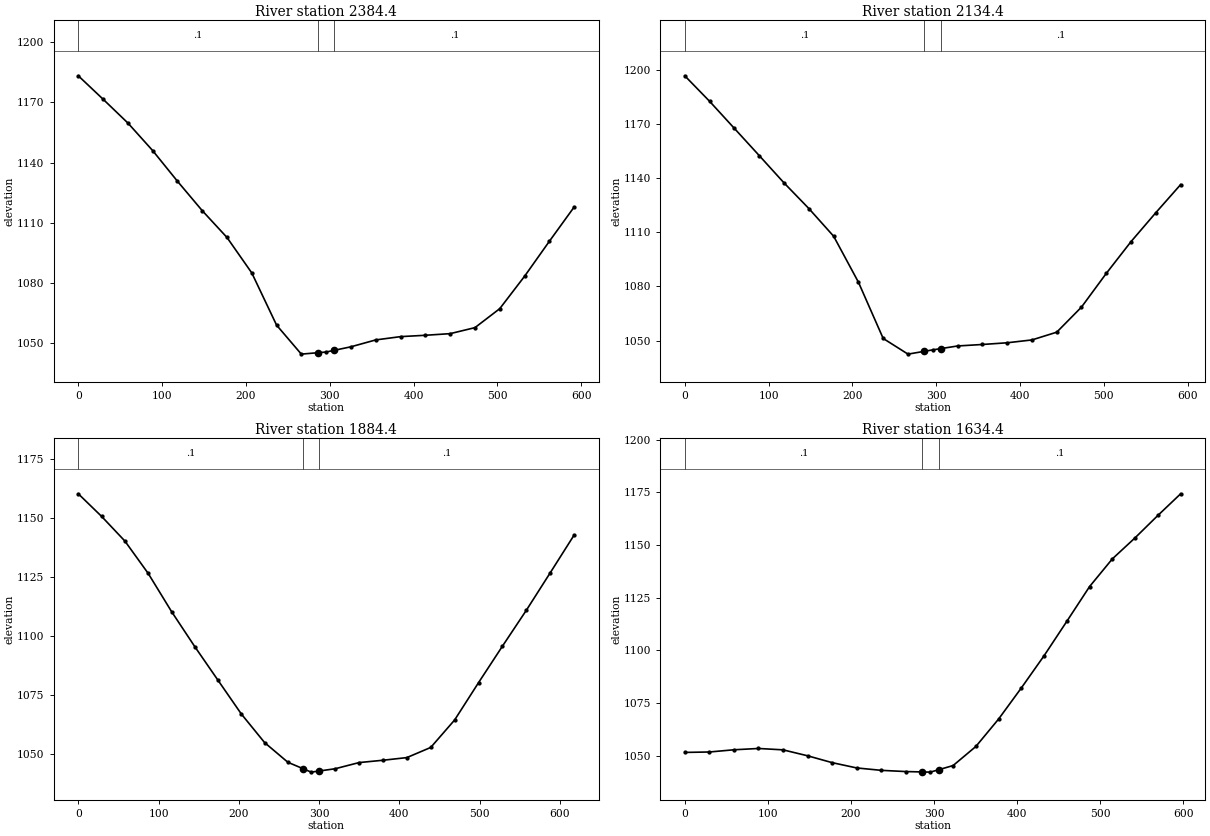
Type RM Length L Ch R = 1 ,2384.4,251.6,250,246.8
XS GIS Cut Line= 3
     1700270.104      426058.332     1700537.340      426184.917
     1700799.732      426321.971
#Sta/Elev= 23
       0 1183.27    29.6 1171.58    59.1 1159.73    88.7 1145.96   118.3 1130.65
   147.8 1116.00   177.4 1102.59   207.0 1084.89   236.6 1058.82   266.1 1044.36
   285.7 1045.06   295.7 1045.41   305.7 1046.29   325.3 1048.02   354.9 1051.45
   384.5 1053.09   414.1 1053.77   443.7 1054.58   473.3 1057.58   502.9 1067.05
   532.5 1083.21   562.1 1100.68   591.7 1117.79
#Mann= 3 , 0 , 0
       0     0.1       0   285.7   0.045       0   305.7     0.1       0
Bank Sta=285.7,305.7
Exp/Cntr=0.3,0.1

Type RM Length L Ch R = 1 ,2134.4,250.3,250,240.6
XS GIS Cut Line= 3
     1700153.251      426301.332     1700428.783      426409.290
     1700705.373      426513.719
#Sta/Elev= 23
       0 1196.75    29.6 1182.62    59.2 1167.58    88.8 1152.54   118.4 1137.39
   148.0 1123.19   177.6 1107.82   207.2 1082.31   236.7 1051.15   266.3 1042.46
   285.9 1044.02   295.9 1044.82   305.9 1045.55   325.5 1046.98   355.1 1047.81
   384.6 1048.75   414.2 1050.33   443.8 1054.63   473.3 1068.53   502.9 1087.22
   532.4 1104.82   562.0 1120.87   591.6 1136.44
#Mann= 3 , 0 , 0
       0     0.1       0   285.9   0.045       0   305.9     0.1       0
Bank Sta=285.9,305.9
Exp/Cntr=0.3,0.1

Type RM Length L Ch R = 1 ,1884.4,251.6,250,255.7
XS GIS Cut Line= 3
     1700056.010      426537.226     1700328.188      426637.722
     1700655.730      426639.925
#Sta/Elev= 24
       0 1160.20    29.0 1150.62    58.0 1140.16    87.0 1126.45   116.1 1110.26
   145.1 1095.35   174.1 1081.05   203.1 1066.77   232.1 1054.64   261.1 1046.29
   280.1 1043.56   290.1 1042.12   300.1 1042.60   319.9 1043.55   349.7 1046.17
   379.5 1047.16   409.2 1048.28   439.0 1052.59   468.8 1064.25   498.6 1080.09
   528.4 1095.59   558.1 1110.78   587.9 1126.70   617.7 1142.73
#Mann= 3 , 0 , 0
       0     0.1       0   280.1   0.045       0   300.1     0.1       0
Bank Sta=280.1,300.1
Exp/Cntr=0.3,0.1

Type RM Length L Ch R = 1 ,1634.4,1649,1634.4,1613.1
XS GIS Cut Line= 3
     1700056.001      426829.553     1700350.076      426859.123
     1700646.973      426910.815
#Sta/Elev= 24
       0 1051.56    29.6 1051.76    59.1 1052.81    88.7 1053.43   118.2 1052.78
   147.8 1049.96   177.3 1046.71   206.9 1044.19   236.4 1043.05   266.0 1042.47
   285.6 1042.29   295.6 1042.20   305.6 1043.34   323.0 1045.32   350.4 1054.38
   377.8 1067.42   405.1 1082.15   432.5 1097.46   459.9 1113.80   487.3 1130.31
   514.7 1143.45   542.1 1153.46   569.5 1164.07   596.9 1174.34
#Mann= 3 , 0 , 0
       0     0.1       0   285.6   0.045       0   305.6     0.1       0
Bank Sta=285.6,305.6
Exp/Cntr=0.3,0.1